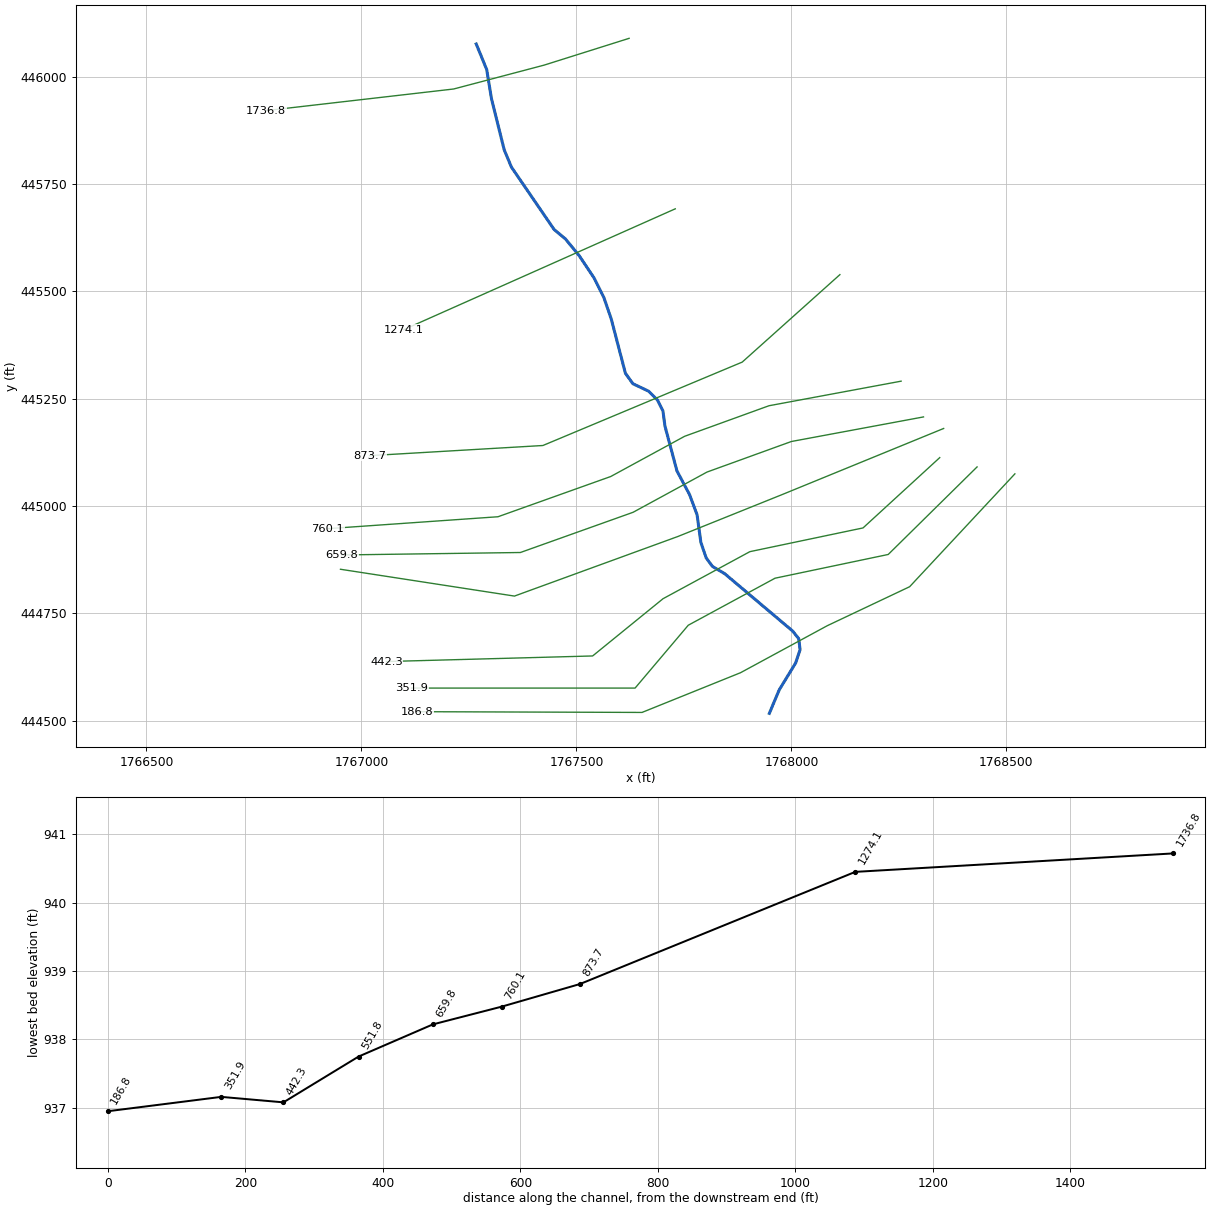
--- RobertsRun.prj (project) ---

Proj Title=RobertsRun
Current Plan=p01
Default Exp/Contr=0,0
English Units
Geom File=g01
Flow File=f01
Plan File=p01
BEGIN DESCRIPTION:
END DESCRIPTION:
DSS Export Rating Curves= 0
DSS Export Rating Curve Sorted= 0
DSS Export Volume Flow Curves= 0
DXF OffsetX= 0
DXF OffsetY= 0
DXF ScaleX= 0
DXF ScaleY= 0

--- RobertsRun.p01 (plan) ---

Plan Title=Floodplain
Program Version=4.00
Geom File=g01
Flow File=f01
K Sum by GR=0
Std Step Tol=0.01
Critical Tol=0.01
Num of Std Step Trials=20
Max Error Tol=0.3
Flow Tol Ratio=0.001
Split Flow NTrial=30
Split Flow Tol=0.02
Split Flow Ratio=0.02
Log Output Level=0
Friction Slope Method=1
Unsteady Friction Slope Method=2
Unsteady Bridges Friction Slope Method=1
Global Log Level=0
CheckData=False
Run HTab=0
Run UNet=0
Run PostProcess=0
UNET Theta=0
UNET Theta Warmup=0
UNET ZTol=0
UNET ZSATol=0
UNET MxIter=0
UNET MaxInSteps=0
UNET DtIC=0
UNET DtMin=0
UNET MaxCRTS=0
UNET WFStab=0
UNET SFStab=0
UNET WFX=0
UNET SFX=0
UNET DSS MLevel=0
UNET DZMax Abort=0
UNET Convert EG Bridges=0
UNET Use Existing IB Tables=0
UNET Froude Limit=0
UNET Froude Power=0
Write IC File=0
Echo Input=False
Echo Output=False
Write Detailed=0

--- RobertsRun.f01 (steady flow) ---

Flow Title=NFF Regression Equation
Program Version=4.10
Number of Profiles= 1
Profile Names=P100yr
River Rch & RM=RobertsRun,Main            ,1736.8
    3011
River Rch & RM=RobertsRun,Main            ,551.8
    3021
Boundary for River Rch & Prof#=RobertsRun,Main            , 1
Up Type= 0
Dn Type= 3
Dn Slope=0.00128
DSS Import GetInterval= 0
DSS Import GetPeak= 0
DSS Import FillOption= 0

--- RobertsRun.g01 (geometry) ---

Geom Title=USGS 10m DEM
Program Version=4.10

River Reach=RobertsRun      ,Main
Reach XY= 30
     1767267.059      446076.616      1767291.34      446017.302
     1767302.404      445949.811       1767332.1      445830.027
     1767348.956      445789.651     1767448.238      445644.255
     1767474.472      445622.393     1767506.376      445583.549
     1767541.098      445531.466     1767563.667      445486.327
     1767581.028       445435.98     1767614.015      445309.244
     1767631.375      445284.938     1767667.834      445267.577
     1767688.667      445246.744     1767701.334       445221.41
     1767706.028       445185.98     1767733.806      445081.814
      1767763.32      445026.258     1767780.681      444979.383
     1767789.545      444914.902     1767801.893      444878.886
     1767816.476      444859.068     1767844.917       444842.23
     1768002.903       444708.55     1768017.118      444690.679
     1768020.264      444665.147     1768009.848      444633.897
     1767971.653      444571.397     1767948.743      444516.657

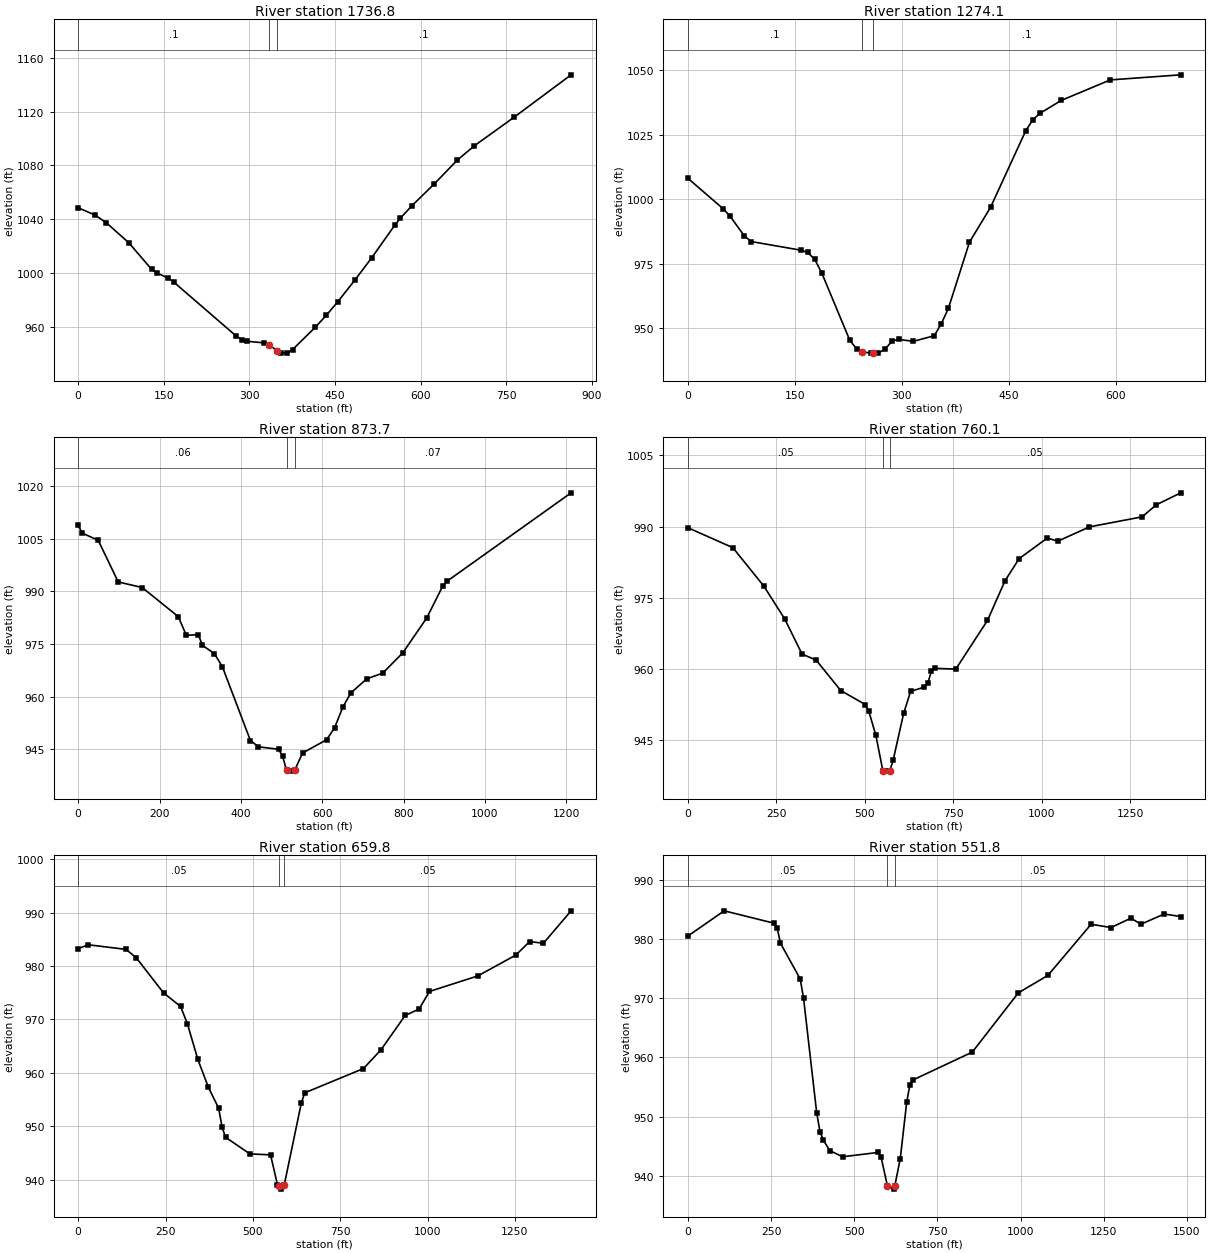
Type RM Length L Ch R = 1 ,1736.8  ,459.6,462.8,465.8
XS GIS Cut Line= 4
     1767622.632      446089.836     1767424.715      446027.336
     1767214.645       445971.78     1766778.882      445921.433
#Sta/Elev= 30
       0  1048.6    29.6 1043.18    49.4 1037.46      89 1022.53   128.5 1002.95
   138.4 1000.14   158.1  996.29     168  993.24   276.7  953.46   286.6  950.77
   296.4  949.48   326.1  948.34   333.9  946.87   348.9  942.54   355.7  940.84
   365.6  940.72   375.5  943.35     415  959.75   434.8  968.84   454.8  978.89
   484.7  994.93   514.6  1011.7   554.4 1035.56   564.4  1040.9   584.4 1050.03
   624.2 1066.47   664.1 1083.98     694  1094.6   763.8 1115.87   863.5  1147.3
#Mann= 3 , 0 , 0
       0      .1       0   333.9    .045       0   348.9      .1       0
Bank Sta=333.9,348.9
XS Rating Curve= 0 ,0
Exp/Cntr=0.3,0.1

Type RM Length L Ch R = 1 ,1274.1  ,400.6,400.4,400.2
XS GIS Cut Line= 2
     1767729.956      445692.521     1767098.907      445411.107
#Sta/Elev= 30
       0 1008.22    49.4  996.42    59.2  993.52      79  985.92    88.8   983.7
   157.9  980.37   167.8  979.53   177.7  976.83   187.5  971.64     227  945.44
   236.9  941.97   244.8  940.93   256.6  940.45   259.8  940.46   266.5  940.47
   276.4  941.91   286.2  945.18   296.1  945.77   315.9     945   345.5   947.2
   355.4  951.92   365.2  957.78   394.8  983.47   424.4  997.02   473.8 1026.73
   483.7 1030.91   493.5 1033.37   523.2 1038.37   592.2 1046.35     691 1048.32
#Mann= 3 , 0 , 0
       0      .1       0   244.8    .045       0   259.8      .1       0
Bank Sta=244.8,259.8
XS Rating Curve= 0 ,0
Exp/Cntr=0.3,0.1

Type RM Length L Ch R = 1 ,873.7   ,111.1,113.6,116.6
XS GIS Cut Line= 4
     1768112.851      445539.141     1767885.709      445335.329
     1767422.147      445140.932     1767019.101      445117.266
#Sta/Elev= 30
       0 1008.84     9.8 1006.53    49.2  1004.5    98.4  992.65   157.5  991.04
   246.1  982.76   265.8  977.45   295.3  977.65   305.2  974.63   334.8  972.24
   354.5   968.5   423.4  947.51   443.2  945.73   492.4  945.03   502.3  943.12
   512.2  939.06     522  938.81   531.9  938.99   551.6  943.97   610.7  947.75
   630.4  951.18   650.2  956.94   669.9  961.02   709.3  965.06   748.7  966.71
     798  972.47   857.1  982.45   896.5  991.57   906.3  992.82  1211.6    1018
#Mann= 3 , 0 , 0
       0     .06       0   512.2    .045       0   531.9     .07       0
Bank Sta=512.2,531.9
XS Rating Curve= 0 ,0
Exp/Cntr=0.3,0.1

Type RM Length L Ch R = 1 ,760.1   ,100,100.3,99.8
XS GIS Cut Line= 6
     1768255.213      445290.877     1767947.921      445233.586
      1767751.74      445162.405     1767579.865      445068.655
     1767317.713      444974.905     1766921.879      444947.127
#Sta/Elev= 30
       0  989.75     127  985.55   214.9  977.42   273.5  970.54   322.5  963.13
   362.3  961.87   431.8  955.46   501.4  952.49   511.3  951.04   531.1     946
   550.6  938.61   560.4  938.48  570.32   938.5     580  940.83   609.4  950.62
     629  955.26   668.1   956.2   677.9  957.07   687.7  959.48   697.5  960.13
   756.8  959.97   846.3  970.22     896   978.6   935.8  983.24  1015.3  987.58
  1045.1  986.92  1134.4  989.93  1283.2  992.04  1322.8  994.56  1392.3   997.1
#Mann= 3 , 0 , 0
       0     .05       0   550.6    .045       0  570.32     .05       0
Bank Sta=550.6,570.32
XS Rating Curve= 0 ,0
Exp/Cntr=0.3,0.1

Type RM Length L Ch R = 1 ,659.8   ,110.6,108,105.5
XS GIS Cut Line= 6
     1768307.296      445207.544     1768000.004      445150.252
     1767803.824      445079.072     1767631.949      444985.322
     1767369.796      444891.572     1766954.594      444885.857
#Sta/Elev= 30
       0  983.28    29.3  983.98   136.8  983.12   166.1  981.56   244.2  974.98
     293  972.43   312.6  969.18   342.4  962.53   372.2  957.36     402  953.37
     412  949.79   421.9  947.92   491.5  944.82   550.6  944.64   570.2  939.08
   574.3  938.72     580  938.22   589.8  939.02   638.8   954.4   648.5  956.26
   816.5   960.8   866.2  964.28   935.8  970.74   975.6  971.94  1005.4  975.24
  1143.8  978.15  1252.5  982.05  1292.1  984.58  1331.6  984.27  1410.7  990.34
#Mann= 3 , 0 , 0
       0     .05       0   574.3    .045       0   589.8     .05       0
Bank Sta=574.3,589.8
XS Rating Curve= 0 ,0
Exp/Cntr=0.3,0.1

Type RM Length L Ch R = 1 ,551.8   ,108.4,109.4,111
XS GIS Cut Line= 5
     1768354.171      445180.634     1767977.435       445026.12
     1767736.115      444928.898     1767355.907      444790.009
     1766951.393      444852.509
#Sta/Elev= 30
       0  980.48   109.2  984.74   258.2  982.66   268.2   981.9   278.1  979.29
   337.7  973.22   347.6  970.03   387.3  950.58   397.3  947.39   407.2  946.02
   426.5  944.26     465  943.21     571  943.94   580.6  943.16   599.9  938.27
   619.2  937.75   622.1  938.35   638.4  942.92   657.7  952.43   667.4  955.41
   677.2   956.2   854.9  960.89   993.2  970.89  1082.1  973.84  1211.9  982.47
  1271.8  981.92  1331.7   983.5  1361.7  982.48  1431.5   984.2  1481.4  983.78
#Mann= 3 , 0 , 0
       0     .05       0   599.9    .045       0   622.1     .05       0
Bank Sta=599.9,622.1
XS Rating Curve= 0 ,0
Exp/Cntr=0.3,0.1

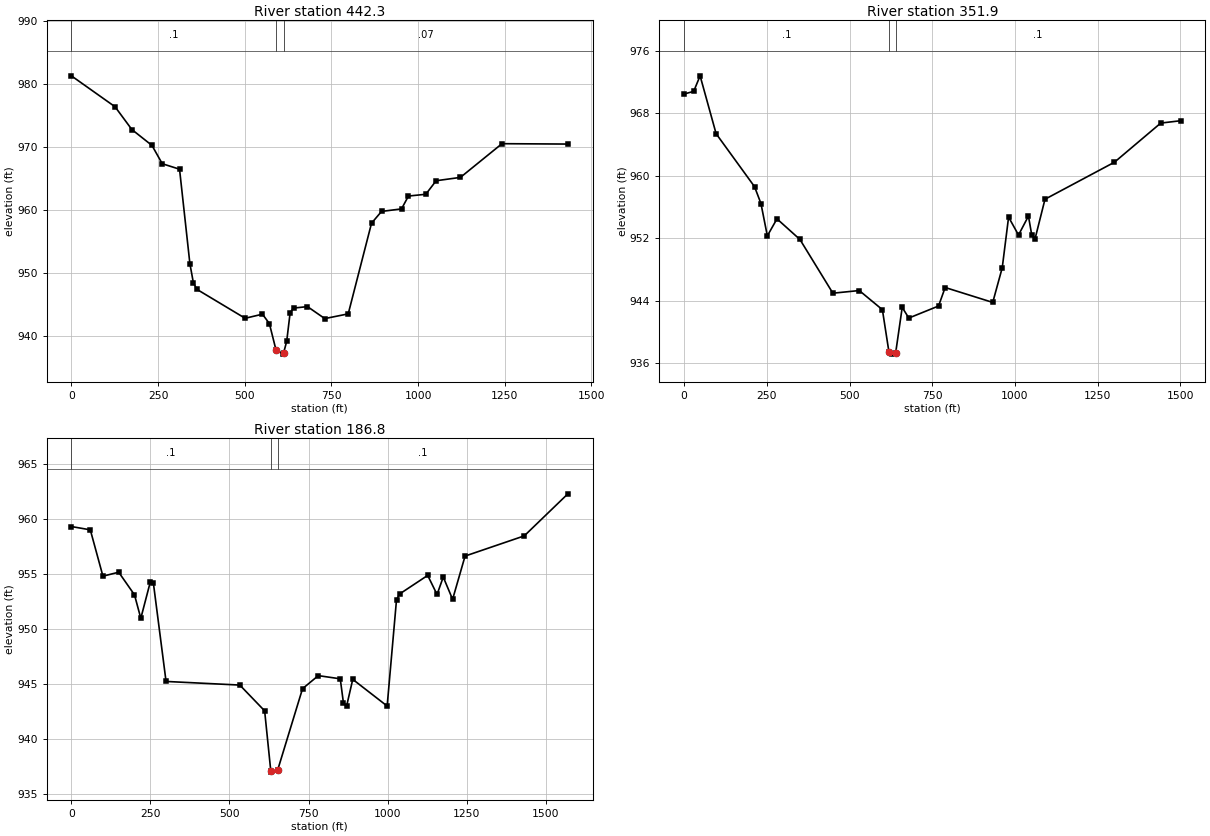
Type RM Length L Ch R = 1 ,442.3   ,88.9,90.4,90.7
XS GIS Cut Line= 6
     1768345.056      445112.709     1768166.671      444948.863
     1767903.433      444893.525      1767701.61      444783.933
     1767537.765      444650.469     1767058.164      444637.449
#Sta/Elev= 30
       0  981.25     126  976.34   174.4  972.73   232.5   970.2   262.1   967.3
     312  966.43   341.8  951.45   351.8  948.43   361.8  947.37   501.2  942.77
   551.1  943.42   571.1  941.93   590.5  937.67   611.1  937.08  611.89  937.23
     621   939.1     631  943.67     641  944.39     681  944.62   730.9  942.72
   798.5  943.47   865.7  957.86   894.6  959.73   952.2  960.13   972.2  962.17
  1022.2  962.45  1052.1   964.6  1122.1  965.13    1242  970.48    1432  970.42
#Mann= 3 , 0 , 0
       0      .1       0   590.5    .045       0  611.89     .07       0
Bank Sta=590.5,611.89
XS Rating Curve= 0 ,0
Exp/Cntr=0.3,0.1

Type RM Length L Ch R = 1 ,351.9   ,164.8,165.1,165.7
XS GIS Cut Line= 6
     1768431.862      445091.008     1768225.265      444887.014
     1767962.027      444831.676     1767760.204      444722.084
     1767636.506        444575.6     1767116.758        444575.6
#Sta/Elev= 30
       0  970.46      29   970.8    48.4  972.79    96.8  965.38   212.9   958.6
   232.3  956.44   251.6   952.3   280.7  954.48   350.1  951.84   449.7  944.96
   529.4   945.3   599.3  942.85   619.2  937.41   629.2  937.16   639.3  937.29
   659.2  943.14   679.2  941.78     769  943.32     789  945.69   932.8  943.78
   961.5  948.22   980.7   954.7  1010.7  952.41  1040.7  954.83  1050.7  952.41
  1060.7  951.93  1090.7  956.99  1300.6  961.73  1440.5  966.74  1500.5  967.04
#Mann= 3 , 0 , 0
       0      .1       0   619.2    .045       0   639.3      .1       0
Bank Sta=619.2,639.3
XS Rating Curve= 0 ,0
Exp/Cntr=0.3,0.1

Type RM Length L Ch R = 1 ,186.8   ,206.9,186.8,165.7
XS GIS Cut Line= 6
     1768519.807      445074.839     1768275.015      444811.818
     1768083.555      444720.999     1767881.732      444611.407
     1767652.619      444518.849     1767130.484      444520.585
#Sta/Elev= 30
       0  959.32    59.9  959.02    99.8   954.8   149.7  955.16   199.6   953.1
   219.6  950.96   249.5  954.26   259.5  954.14   299.4  945.21   532.7  944.88
   611.2  942.53  630.76  937.01   631.1  936.95   652.3  937.13     731  944.55
   780.9  945.74   850.3  945.45   860.2  943.29   870.1  942.93   889.8   945.4
   998.6  942.97  1028.2  952.65  1038.1  953.18  1126.8  954.87  1156.4  953.13
    1176  954.72  1205.6  952.69    1245  956.63  1432.2  958.47  1570.1   962.3
#Mann= 3 , 0 , 0
       0      .1       0  630.76    .045       0   652.3      .1       0
Bank Sta=630.76,652.3
XS Rating Curve= 0 ,0
Exp/Cntr=0.3,0.1

Chan Stop Cuts=-1
Use User Specified Reach Order=0
Composite Channel Slope=5